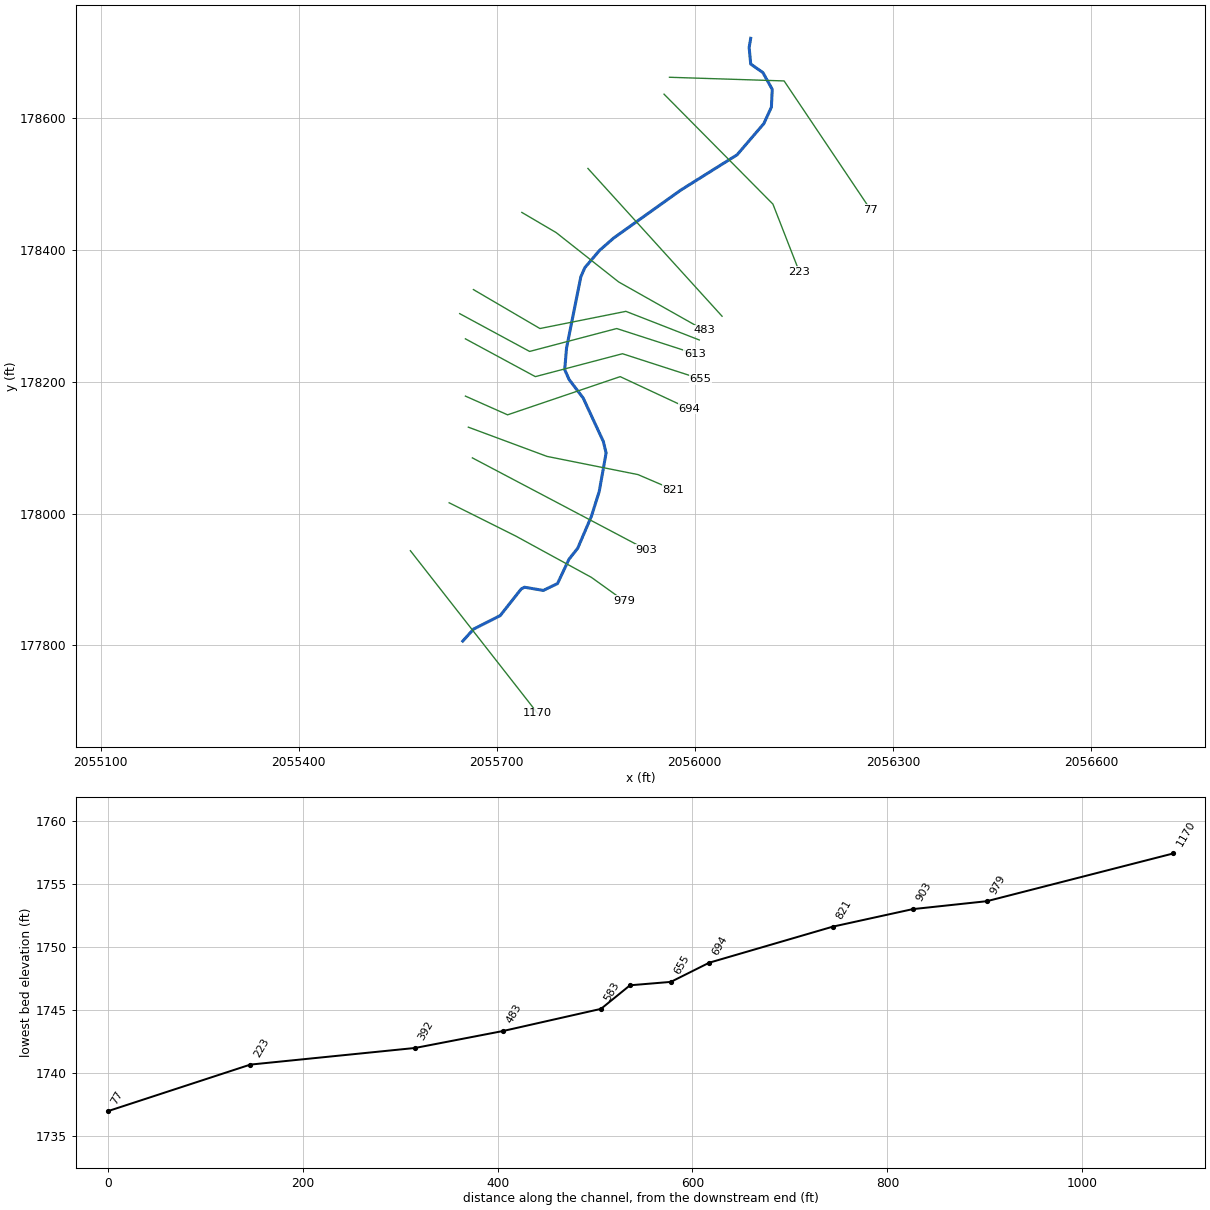
--- BLKLCKT1.prj (project) ---

Proj Title=BLKLCKT1
Current Plan=p01
Default Exp/Contr=0,0
English Units
Geom File=g01
Flow File=f01
Plan File=p01
Background Map Layer=Inundation Boundary (01pct Value_0)
BEGIN DESCRIPTION:
Stream Name: Blue Lick Creek Tributary
Flood Zone: Approximate
Monroe County, West Virginia
HEC-RAS Version: 5.0.7
Vertical Datum: NAVD88
Projection: NAD 1983 StatePlane West Virginia S FIPS 4702 (US Feet)
LiDAR: 2016, 1-meter
Land Use: 2016 NLCD
Hydrology Method:
Regression.
Model Notes:
END DESCRIPTION:
DSS Export Rating Curves= 0
DSS Export Rating Curve Sorted= 0
DSS Export Volume Flow Curves= 0
DXF OffsetX= 0
DXF OffsetY= 0
DXF ScaleX= 0
DXF ScaleY= 0

--- BLKLCKT1.p01 (plan) ---

Plan Title=Floodplain
Program Version=5.07
Short Identifier=Floodplain
Geom File=g01
Flow File=f01
Subcritical Flow
K Sum by GR= 0
Std Step Tol= 0.01
Critical Tol= 0.01
Num of Std Step Trials= 20
Max Error Tol= 0.3
Flow Tol Ratio= 0.001
Split Flow NTrial= 30
Split Flow Tol= 0.02
Split Flow Ratio= 0.02
Log Output Level= 0
Friction Slope Method= 1
Unsteady Friction Slope Method= 2
Unsteady Bridges Friction Slope Method= 1
Parabolic Critical Depth
Global Vel Dist= 0 , 0 , 0
Global Log Level= 0
CheckData=True
Encroach Param=-1 ,0,0, 0
Mapping Interval=1HOUR
Computation Time Step Use Courant=        0
Computation Time Step Use Time Series=    0
Computation Time Step Count To Double=0
Computation Time Step Max Doubling=0
Computation Time Step Max Halving=0
Computation Time Step Residence Courant=0
Run HTab= 0
Run UNet= 0
Run Sediment= 0
Run PostProcess= 0
Run WQNet= 0
Run RASMapper=-1
UNET Theta= 0
UNET Theta Warmup= 0
UNET ZTol= 0
UNET ZSATol= 0
UNET MxIter= 0
UNET Max Iter WO Improvement= 0
UNET MaxInSteps= 0
UNET DtIC= 0
UNET DtMin= 0
UNET MaxCRTS= 0
UNET WFStab= 0
UNET SFStab= 0
UNET WFX= 1
UNET SFX= 1
UNET 1D Methodology=Finite Difference
UNET DSS MLevel= 1
UNET Pardiso=0
UNET DZMax Abort= 0
UNET Use Existing IB Tables= 0
UNET Froude Reduction=False
UNET Froude Limit= 0
UNET Froude Power= 0
UNET D1 Cores= 0
UNET D2 Coriolis=0
UNET D2 Cores= 0
UNET D2 Theta= 1
UNET D2 Theta Warmup= 1
UNET D2 Z Tol= 0.01
UNET D2 Volume Tol= 0.01
UNET D2 Max Iterations= 20
UNET D2 Equation= 0
UNET D2 RampUpFraction=0.1
UNET D2 TimeSlices= 1
UNET D2 BCVolumeCheck=0
UNET D1D2 MaxIter= 0
UNET D1D2 ZTol=0.01
UNET D1D2 QTol=0.1
UNET D1D2 MinQTol=1
Write IC File= 0
Write IC File at Fixed DateTime=0
Write IC File at Sim End=0
Echo Input=False
Echo Parameters=False
Echo Output=False
Write Detailed= 0
HDF Write Warmup=0
HDF Write Time Slices=0
HDF Flush=0
HDF Face Node Velocities=0
HDF Compression= 1
HDF Chunk Size= 1
HDF Spatial Parts= 1
HDF Use Max Rows=0
HDF Fixed Rows= 1
Calibration Method= 0
Calibration Iterations= 20
Calibration Max Change=0.05
Calibration Tolerance=0.2
Calibration Maximum=1.5
Calibration Minimum=0.5
Calibration Optimization Method= 1
WQ AD Non Conservative
WQ ULTIMATE=-1
WQ Max Comp Step=1HOUR
WQ Output Interval=15MIN
WQ Output Selected Increments= 0
WQ Output face flow=0
WQ Output face velocity=0
WQ Output face area=0
WQ Output face dispersion=0
WQ Output cell volume=0
WQ Output cell surface area=0
WQ Output cell continuity=0
WQ Output cumulative cell continuity=0
WQ Output face conc=0
WQ Output face dconc_dx=0
WQ Output face courant=0
WQ Output face peclet=0
WQ Output face adv mass=0
WQ Output face disp mass=0
WQ Output cell mass=0
WQ Output cell source sink temp=0
WQ Output nsm pathways=0
WQ Output nsm derived pathways=0
WQ Output MaxMinRange=-1
WQ Daily Max Min Mean=-1
WQ Daily Range=0
WQ Daily Time=0
WQ Create Restart=0
WQ Fixed Restart=0
WQ System Summary=0
WQ Write To DSS=0
WQ Use Fixed Temperature=0
Sorting and Armoring Iterations= 10
XS Update Threshold= 0.02
Bed Roughness Predictor= 0
Hydraulics Update Threshold= 0.02
Energy Slope Method= 1
Volume Change Method= 1
Sediment Retention Method= 0
XS Weighting Method= 0
Number of US Weighted Cross Sections= 1
Number of DS Weighted Cross Sections= 1
Upstream XS Weight=0
Main XS Weight=1
Downstream XS Weight=0
Number of DS XS's Weighted with US Boundary= 1
Upstream Boundary Weight= 1
Weight of XSs Associated with US Boundary= 0
Number of US XS's Weighted with DS Boundary= 1
Downstream Boundary Weight= 0.5
Weight of XSs Associated with DS Boundary= 0.5
Percentile Method= 0
Sediment Output Level= 3
Mass or Volume Output= 0
Output Increment Type= 1
Profile and TS Output Increment= 1
XS Output Flag= 0
XS Output Increment= 10
Write Gradation File= 0
Read Gradation Hotstart= 0
Write HDF5 File= 1
Write Binary Output= 1
Write DSS Sediment File= 0
SV Curve= 0
Specific Gage Flag= 0

--- BLKLCKT1.f01 (steady flow) ---

Flow Title=Flow
Program Version=5.07
Number of Profiles= 6
Profile Names=01pct,10pct,04pct,02pct,0_2pct,01plus
River Rch & RM=BLKLCKT1,Main            ,1170
     555     293     390     470     776     821
Boundary for River Rch & Prof#=BLKLCKT1,Main            , 1
Up Type= 0
Dn Type= 3
Dn Slope=0.0238
Boundary for River Rch & Prof#=BLKLCKT1,Main            , 2
Up Type= 0
Dn Type= 3
Dn Slope=0.0238
Boundary for River Rch & Prof#=BLKLCKT1,Main            , 3
Up Type= 0
Dn Type= 3
Dn Slope=0.0238
Boundary for River Rch & Prof#=BLKLCKT1,Main            , 4
Up Type= 0
Dn Type= 3
Dn Slope=0.0238
Boundary for River Rch & Prof#=BLKLCKT1,Main            , 5
Up Type= 0
Dn Type= 3
Dn Slope=0.0238
Boundary for River Rch & Prof#=BLKLCKT1,Main            , 6
Up Type= 0
Dn Type= 3
Dn Slope=0.0238
DSS Import GetInterval= 0
DSS Import GetPeak= 0
DSS Import FillOption= 0

--- BLKLCKT1.g01 (geometry) ---

Geom Title=Geometry
Program Version=5.07

River Reach=BLKLCKT1        ,Main
Reach XY= 30
     2055648.577      177806.688      2055665.07      177824.917
     2055705.278      177845.241     2055737.118      177885.681
     2055742.084      177888.297     2055770.556      177883.436
     2055792.084      177893.852     2055809.445      177930.658
     2055822.639      177947.325     2055843.472      177995.935
     2055855.278      178033.436     2055865.695      178091.769
     2055861.528       178109.13     2055830.972      178175.102
     2055809.609      178203.208     2055802.988      178218.177
     2055805.766      178250.816     2055827.396      178358.771
     2055833.472       178372.66     2055855.608      178398.702
     2055876.875      178417.365     2055978.872      178490.282
     2056064.088      178543.777     2056104.584      178591.074
     2056116.034      178616.013     2056117.294      178643.003
     2056103.189      178668.322     2056084.688      178681.361
     2056082.332       178706.48     2056084.676      178720.285

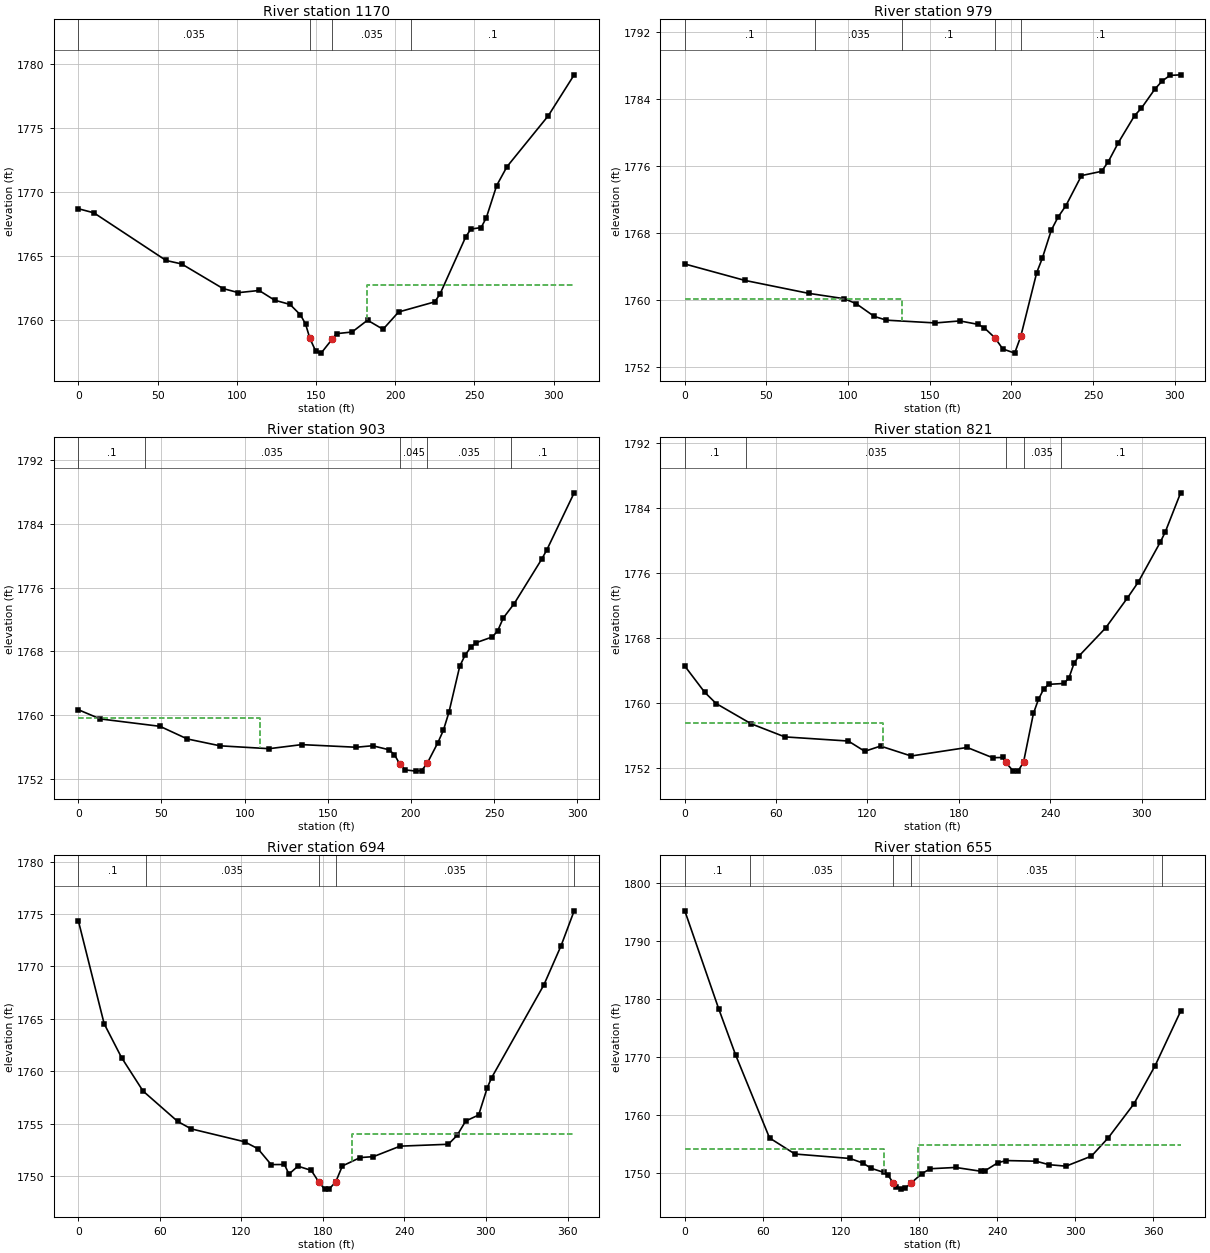
Type RM Length L Ch R = 1 ,1170    ,154.5,191.4,181.9
XS GIS Cut Line= 2
     2055569.296       177943.61     2055762.004      177697.083
#Sta/Elev= 30
       0  1768.7     9.8 1768.38    55.4 1764.66    65.2 1764.39    91.3 1762.47
     101 1762.15   114.1 1762.32   123.9 1761.56   133.6 1761.23   140.2 1760.41
   143.4  1759.7  146.131758.576   149.9 1757.56   153.2 1757.43   160.2 1758.52
     163 1758.95   172.8 1759.08   182.5    1760   192.3 1759.29   202.1 1760.64
   224.9 1761.43   228.2 1762.03   244.5 1766.51   247.7 1767.11   254.2 1767.23
   257.5 1768.01     264 1770.51   270.5 1771.98   296.6 1775.96   312.9 1779.15
#Mann= 4 ,-1 , 0
       0    .035       0  146.13    .045       0   160.2    .035       0
     210      .1       0
#XS Ineff= 2 , 0
                           182.4         1762.77
Permanent Ineff=
       F       F
Bank Sta=146.13,160.2
XS Rating Curve= 0 ,0
Exp/Cntr=0.3,0.1

Type RM Length L Ch R = 1 ,979     ,74.9,76.1,76.3
XS GIS Cut Line= 4
2055628.01081533178016.279997752 2055728.8797002177965.845555315
2055843.50343301177903.1845813782055892.40955901177868.033303316
#Sta/Elev= 30
       0  1764.3    36.7 1762.34    75.8 1760.79    97.6 1760.15   104.9 1759.56
     116 1758.03   123.5 1757.58   153.4 1757.25   168.4 1757.49   179.6 1757.08
   183.3 1756.68   189.9 1755.47   194.7 1754.14     202 1753.64   205.7 1755.63
   215.5 1763.28   218.9 1764.98   224.4 1768.34   228.5 1769.89   233.4 1771.29
   242.9 1774.87   255.2 1775.38   259.3 1776.53   265.5 1778.82   275.4 1782.04
   279.5 1782.91   287.9 1785.23   292.4  1786.2   297.1 1786.85   303.6 1786.92
#Mann= 5 ,-1 , 0
       0      .1       0      80    .035       0  132.77      .1       0
   189.9    .045       0   205.7      .1       0
#XS Ineff= 2 , 0
          132.88 1760.12
Permanent Ineff=
       F       F
Bank Sta=189.9,205.7
XS Rating Curve= 0 ,0
Exp/Cntr(USF)=0,0
Exp/Cntr=0.3,0.1

Type RM Length L Ch R = 1 ,903     ,63.4,82,85.4
XS GIS Cut Line= 2
     2055663.162      178084.352     2055926.819       177945.23
#Sta/Elev= 30
       0  1760.7    13.1 1759.55    49.1 1758.62    65.5 1757.04    85.2 1756.18
   114.7 1755.82   134.3 1756.33   167.1    1756   176.9 1756.19   186.7 1755.69
     190 1755.09   193.3 1753.88   196.6 1753.16   203.1 1753.01   206.4 1753.08
   209.7 1753.97   216.2 1756.59   219.5 1758.14   222.8 1760.37   229.3 1766.14
   232.6 1767.57   235.9  1768.5   239.1 1769.09     249 1769.82   252.2 1770.62
   255.5 1772.19   262.1    1774   278.5 1779.52   281.7 1780.73   298.1 1787.86
#Mann= 5 ,-1 , 0
       0      .1       0      40    .035       0   193.3    .045       0
   209.7    .035       0     260      .1       0
#XS Ineff= 2 , 0
          109.32 1759.61
Permanent Ineff=
       F       F
Bank Sta=193.3,209.7
XS Rating Curve= 0 ,0
Exp/Cntr=0.3,0.1

Type RM Length L Ch R = 1 ,821     ,98.6,126.8,130.8
XS GIS Cut Line= 4
2055657.04882764178130.9037305642055776.25750976178086.582553877
2055913.80598914178059.0728580022055967.29706445 178036.14811144
#Sta/Elev= 30
       0 1764.54      13 1761.33    20.6 1759.93    43.6 1757.44    65.7 1755.83
   107.4 1755.32   118.2 1754.06   128.6  1754.7   148.7 1753.48   185.5 1754.53
   202.2 1753.27   208.9  1753.3   210.81752.692   215.6 1751.66   218.9 1751.62
   222.51752.717     229 1758.71   232.3 1760.44   235.7  1761.7     239 1762.29
   249.1  1762.4   252.4 1763.11   255.7 1764.89   258.9 1765.77   276.4 1769.22
   290.7  1772.9   297.8 1774.84   312.3 1779.76   315.6 1781.02   325.7 1785.84
#Mann= 5 ,-1 , 0
       0      .1       0      40    .035       0   210.8    .045       0
   222.5    .035       0  247.18      .1       0
#XS Ineff= 2 , 0
          130.51 1757.57
Permanent Ineff=
       F       F
Bank Sta=210.8,222.5
XS Rating Curve= 0 ,0
Exp/Cntr(USF)=0,0
Exp/Cntr=0.3,0.1

Type RM Length L Ch R = 1 ,694     ,39.4,39.3,39
XS GIS Cut Line= 4
     2055652.629      178177.985     2055716.478      178149.614
     2055887.004      178207.499     2055991.171      178158.888
#Sta/Elev= 30
       0 1774.37      19 1764.54    31.8 1761.31    47.6 1758.12    73.1 1755.22
      83 1754.51   122.3 1753.28   132.1 1752.62   141.9  1751.1   151.7 1751.11
     155 1750.19   161.6 1750.95   171.4 1750.55  176.791749.476   181.2 1748.77
   184.5 1748.76   189.4 1749.44   194.3 1750.97   207.4 1751.77   217.2 1751.86
   236.8 1752.86   272.3 1753.04   278.7 1753.88   285.1 1755.26   294.6 1755.83
     301 1758.45   304.2  1759.4   342.6 1768.24   355.3 1771.99   364.9 1775.31
#Mann= 5 ,-1 , 0
       0      .1       0      50    .035       0  176.79    .045       0
   189.4    .035       0   364.9      .1       0
#XS Ineff= 2 , 0
                          201.15         1754.06
Permanent Ineff=
       F       F
Bank Sta=176.79,189.4
XS Rating Curve= 0 ,0
Exp/Cntr=0.5,0.3

Type RM Length L Ch R = 1 ,655     ,41.2,41.9,43.3
XS GIS Cut Line= 4
     2055652.629      178264.791     2055758.532      178207.499
     2055890.477      178242.221     2056008.532      178204.027
#Sta/Elev= 30
       0 1795.27      26 1778.39      39 1770.42    65.1 1756.07    84.6  1753.3
   126.9 1752.53   136.6 1751.76   143.2 1750.83   152.9 1750.13   156.1 1749.62
  160.321748.284   162.6  1747.6   165.9 1747.24   169.1 1747.36   173.51748.228
   182.1 1749.91   188.6 1750.76   208.1 1750.98   227.6 1750.32   230.9 1750.45
   240.6 1751.81   247.1 1752.17   269.9 1752.06   279.7 1751.46   292.8  1751.2
   312.4 1752.94   325.4 1756.12     345 1761.95   361.3 1768.54   380.9 1777.94
#Mann= 5 ,-1 , 0
       0      .1       0      50    .035       0  160.32    .045       0
   173.5    .035       0  366.84      .1       0
#XS Ineff= 2 , 0
          153.22 1754.21  178.98          1754.9
Permanent Ineff=
       F       F
Bank Sta=160.32,173.5
XS Rating Curve= 0 ,0
Exp/Cntr=0.5,0.3

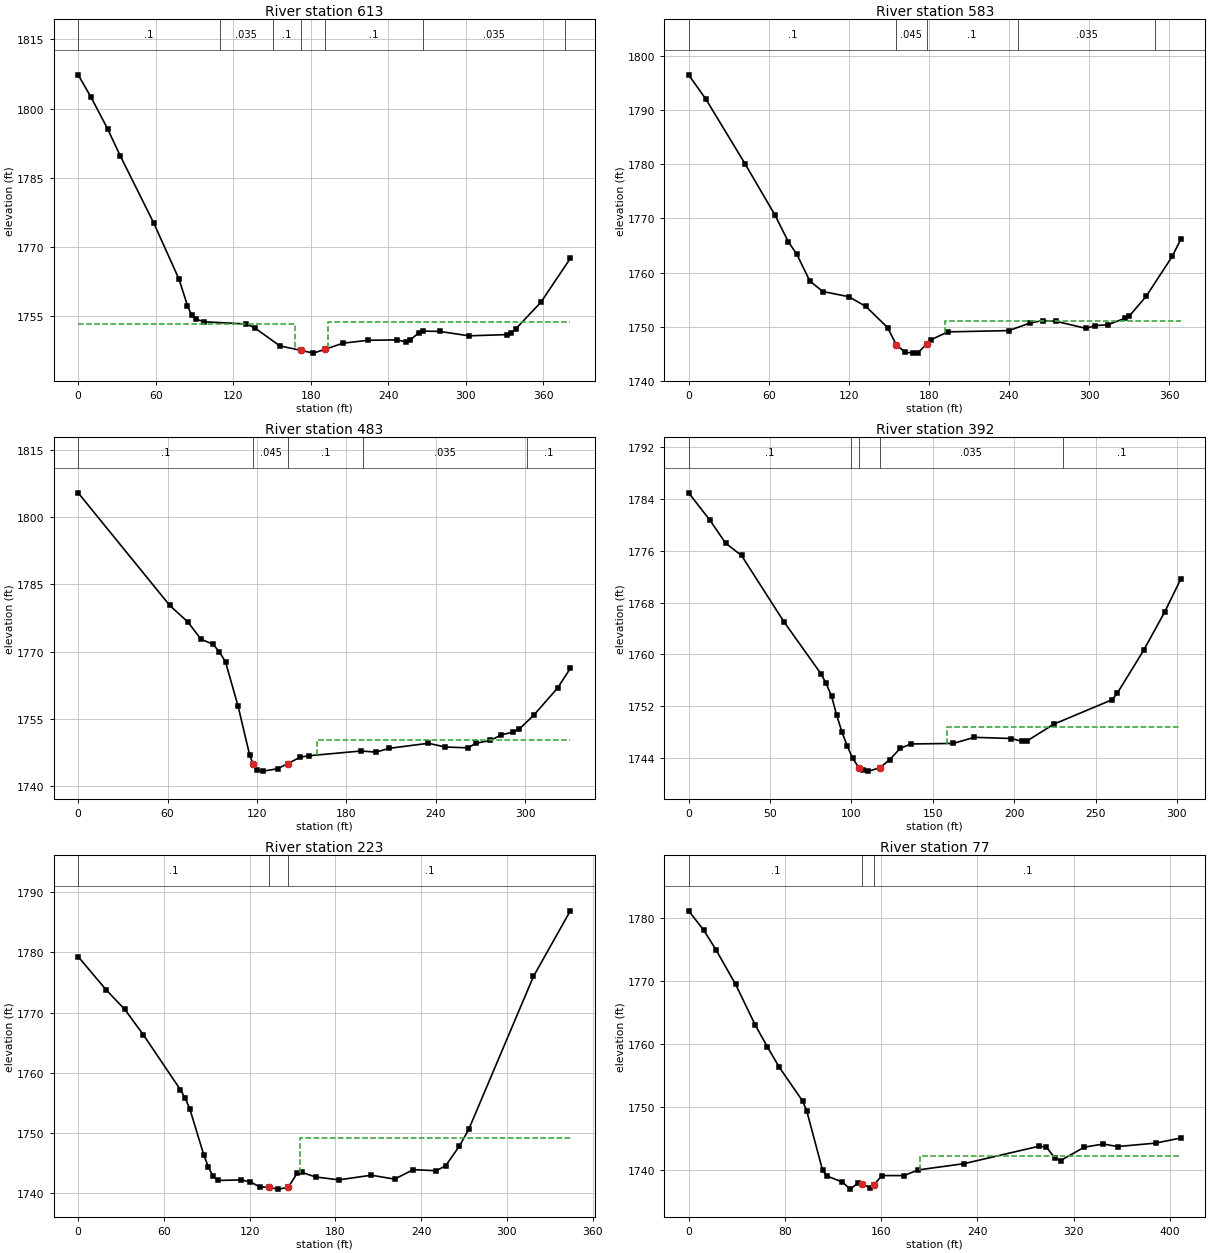
Type RM Length L Ch R = 1 ,613     ,30.5,29.8,29.2
XS GIS Cut Line= 4
     2055643.949      178302.985     2055749.852      178245.694
     2055881.796      178280.416     2055999.852      178242.221
#Sta/Elev= 30
       0 1807.33     9.8 1802.56    22.8 1795.61    32.5 1789.81    58.6 1775.13
    78.1 1762.98    84.6 1757.27    87.9 1755.17    91.1 1754.34    97.6 1753.76
   130.2 1753.29   136.6 1752.46   156.1 1748.54   172.4 1747.57   182.1 1746.97
   190.7 1747.77   204.9 1749.12   224.4 1749.76   247.1 1749.84   253.6 1749.38
   256.8 1749.75   263.4 1751.37   266.6 1751.75   279.7 1751.68   302.6 1750.72
   331.9 1750.99   335.2 1751.38   338.5 1752.18   358.1    1758   380.9 1767.52
#Mann= 7 ,-1 , 0
       0      .1       0     110    .035       0  150.41      .1       0
   172.4    .045       0   190.7      .1       0  266.84    .035       0
  376.84      .1       0
#XS Ineff= 2 , 0
          167.46 1753.36  193.22          1753.7
Permanent Ineff=
       F       F
Bank Sta=172.4,190.7
XS Rating Curve= 0 ,0
Exp/Cntr=0.5,0.3

Type RM Length L Ch R = 1 ,583     ,111.6,100.1,85.7
XS GIS Cut Line= 4
     2055664.782      178339.444     2055765.477      178280.416
     2055895.685      178306.458     2056006.796      178263.055
#Sta/Elev= 30
       0 1796.54      13 1792.02    42.2 1780.13    64.8 1770.58    74.6 1765.73
    81.1 1763.36    90.8 1758.44   100.5 1756.49     120 1755.53   132.9 1753.72
   149.1 1749.81   155.6 1746.64   162.1 1745.28   168.5  1745.1   171.8 1745.15
   178.3 1746.76   181.5 1747.57   194.4 1749.03   239.8 1749.26     256 1750.68
   265.6 1751.12   275.3 1750.98   297.9 1749.67   304.3 1750.18     314 1750.34
   326.9 1751.53   330.1 1751.92     343 1755.65   362.4 1762.99   368.8 1766.16
#Mann= 5 ,-1 , 0
       0      .1       0   155.6    .045       0   178.3      .1       0
  246.72    .035       0  349.51      .1       0
#XS Ineff= 2 , 0
                          191.95         1750.95
Permanent Ineff=
       F       F
Bank Sta=155.6,178.3
XS Rating Curve= 0 ,0
Exp/Cntr=0.3,0.1

Type RM Length L Ch R = 1 ,483     ,92.3,90.5,87.4
XS GIS Cut Line= 4
2055738.04959882178456.435131748 2055790.0123577178425.868802999
2055884.76797682178350.9812975622056014.67487401178277.622108562
#Sta/Elev= 30
       0  1805.4    61.4 1780.32    73.8 1776.54    82.4 1772.76    90.5 1771.64
    94.7 1769.98    98.9  1767.7   107.3 1757.86   115.1 1746.94   117.4 1744.87
   119.8 1743.58     124 1743.35   133.8 1743.87   140.7 1745.03   149.1 1746.47
   154.8 1746.78   189.9 1747.84   199.8 1747.58   208.8 1748.44   235.1 1749.56
   246.4 1748.72   261.5 1748.55   267.1 1749.58   276.6 1750.18   284.1 1751.46
   291.7 1752.02   296.1 1752.75   305.7  1755.8   321.8 1761.91   330.3 1766.26
#Mann= 5 ,-1 , 0
       0      .1       0   117.4    .045       0   140.7      .1       0
  191.06    .035       0  301.06      .1       0
#XS Ineff= 2 , 0
                          160.46         1750.29
Permanent Ineff=
       F       F
Bank Sta=117.4,140.7
XS Rating Curve= 0 ,0
Exp/Cntr(USF)=0,0
Exp/Cntr=0.3,0.1

Type RM Length L Ch R = 1 ,392     ,168.3,169.1,169
XS GIS Cut Line= 2
     2055838.176      178523.037     2056041.301      178299.079
#Sta/Elev= 30
       0 1784.91      13 1780.72    22.8 1777.13    32.5 1775.25    58.5 1765.05
    81.3 1757.02    84.5 1755.52    87.8 1753.57      91  1750.6    94.3 1747.96
    97.5 1745.85   100.8 1743.97  104.651742.536   107.3 1742.11   110.5    1742
   117.4  1742.5   123.5 1743.76     130 1745.51   136.6 1746.19   162.6 1746.27
   175.6 1747.21   198.3 1747.03   204.8  1746.6   208.1 1746.68   224.3 1749.23
   260.1    1753   263.3 1753.99   279.6 1760.64   292.6 1766.59   302.4 1771.62
#Mann= 5 ,-1 , 0
       0      .1       0     100    .035       0  104.65    .045       0
   117.4    .035       0     230      .1       0
#XS Ineff= 2 , 0
                          158.93         1748.87
Permanent Ineff=
       F       F
Bank Sta=104.65,117.4
XS Rating Curve= 0 ,0
Exp/Cntr=0.3,0.1

Type RM Length L Ch R = 1 ,223     ,137.1,146.4,153.6
XS GIS Cut Line= 3
     2055953.411      178635.668     2056118.341      178469.001
     2056158.272       178366.57
#Sta/Elev= 30
       0 1779.29    19.5 1773.79    32.6 1770.53    45.6 1766.32    71.6 1757.17
    74.9 1755.79    78.2 1753.95    87.9 1746.38    91.2 1744.29    94.4  1742.8
    97.7 1742.12     114 1742.21   120.5 1741.88     127 1741.06   133.5 1740.98
     140 1740.68  147.011740.958   153.1 1743.28   156.3 1743.48   166.1  1742.7
   182.4 1742.22   205.2 1742.99   221.4 1742.34   234.5 1743.91   250.6 1743.74
   257.1 1744.54   266.8 1747.85   273.3  1750.6   318.6    1776   344.4 1786.89
#Mann= 3 ,-1 , 0
       0      .1       0   133.5    .045       0  147.01      .1       0
#XS Ineff= 2 , 0
                          155.42         1749.13
Permanent Ineff=
       F       F
Bank Sta=133.5,147.01
XS Rating Curve= 0 ,0
Exp/Cntr=0.3,0.1

Type RM Length L Ch R = 1 ,77      ,77.6,76.3,68.5
XS GIS Cut Line= 3
     2055961.657      178661.2752056135.27666272178655.719646881
2056266.39056027178460.252516329
#Sta/Elev= 30
       0  1781.1  12.4191778.077  22.6991774.941  39.1111769.425  55.5241762.937
  65.3711759.569  75.2191756.341  94.9141750.897  98.298  1749.3 111.3261739.984
 114.6091739.088 127.7391738.108 134.3041736.981 140.8691737.944   144.41737.731
 150.7171737.217   154.2 1737.67 160.5641739.131 178.8291739.126  190.95 1740.03
 228.7821741.014 291.4741743.794 297.3641743.644 304.4461741.889 309.1431741.514
  328.951743.637 344.643 1744.13 356.4651743.731 388.2081744.279 409.0771745.086
#Mann= 3 ,-1 , 0
       0      .1       0   144.4    .045       0   154.2      .1       0
#XS Ineff= 2 , 0
                          192.03          1742.3
Permanent Ineff=
       F       F
Bank Sta=144.4,154.2
XS Rating Curve= 0 ,0
Exp/Cntr=0.3,0.1
LCMann Table=0

Chan Stop Cuts=-1
Use User Specified Reach Order=0
Composite Channel Slope=5